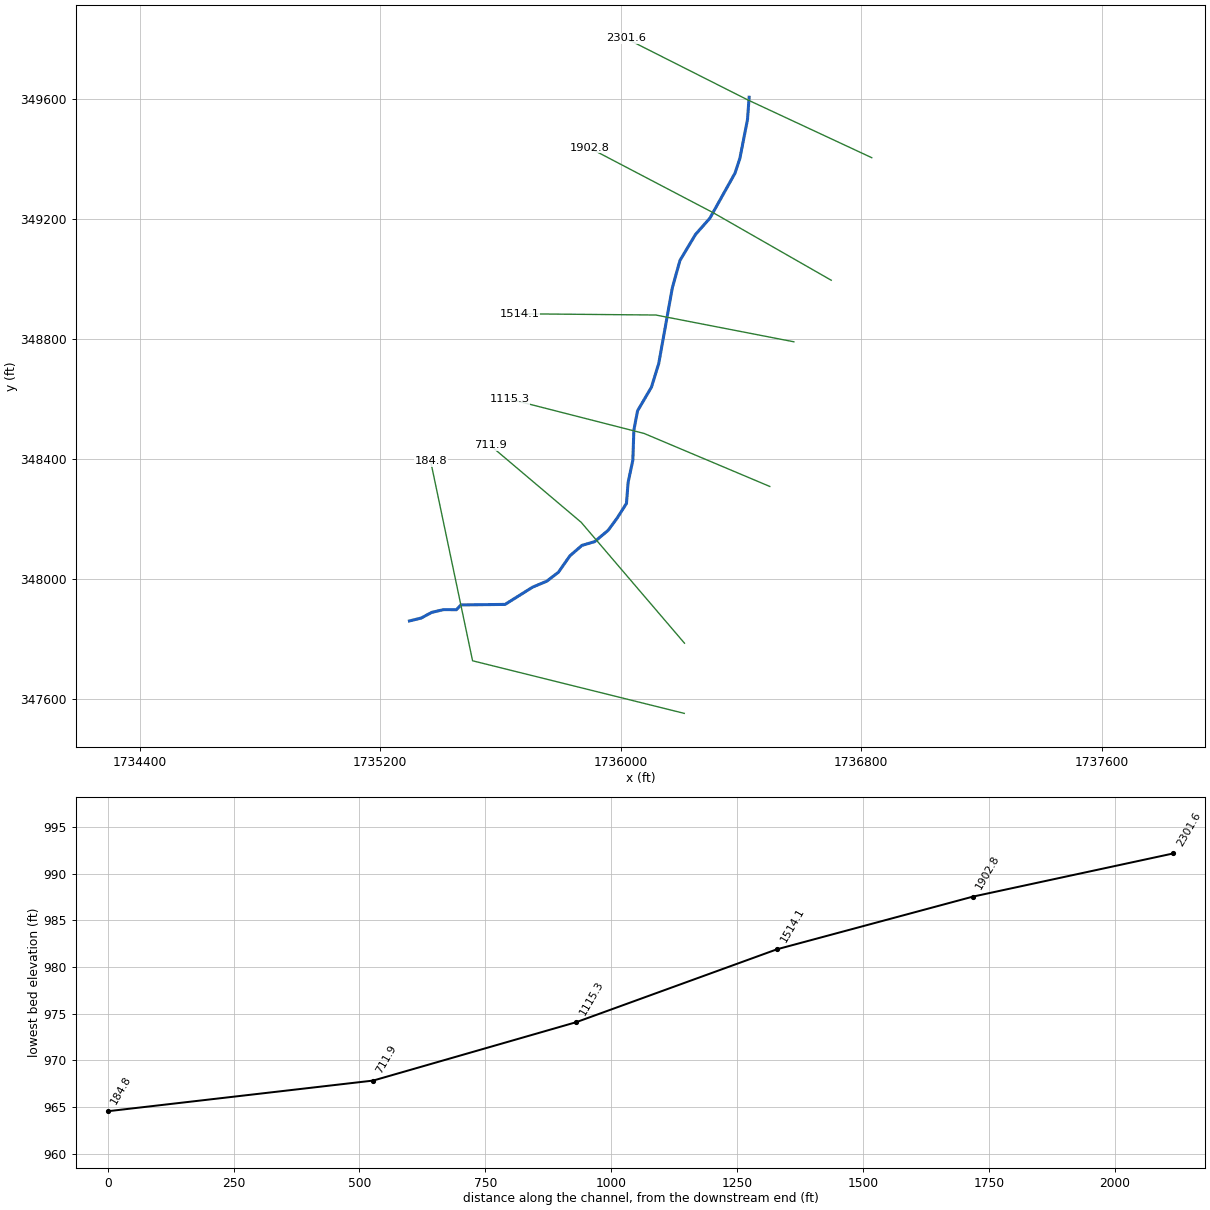
--- NP13.prj (project) ---

Proj Title=NP13
Current Plan=p01
Default Exp/Contr=0,0
English Units
Geom File=g01
Flow File=f01
Plan File=p01
BEGIN DESCRIPTION:
END DESCRIPTION:
DSS Export Rating Curves= 0
DSS Export Rating Curve Sorted= 0
DSS Export Volume Flow Curves= 0
DXF OffsetX= 0
DXF OffsetY= 0
DXF ScaleX= 0
DXF ScaleY= 0

--- NP13.p01 (plan) ---

Plan Title=Floodplain
Program Version=4.00
Geom File=g01
Flow File=f01
K Sum by GR=0
Std Step Tol=0.01
Critical Tol=0.01
Num of Std Step Trials=20
Max Error Tol=0.3
Flow Tol Ratio=0.001
Split Flow NTrial=30
Split Flow Tol=0.02
Split Flow Ratio=0.02
Log Output Level=0
Friction Slope Method=1
Unsteady Friction Slope Method=2
Unsteady Bridges Friction Slope Method=1
Global Log Level=0
CheckData=False
Run HTab=0
Run UNet=0
Run PostProcess=0
UNET Theta=0
UNET Theta Warmup=0
UNET ZTol=0
UNET ZSATol=0
UNET MxIter=0
UNET MaxInSteps=0
UNET DtIC=0
UNET DtMin=0
UNET MaxCRTS=0
UNET WFStab=0
UNET SFStab=0
UNET WFX=0
UNET SFX=0
UNET DSS MLevel=0
UNET DZMax Abort=0
UNET Convert EG Bridges=0
UNET Use Existing IB Tables=0
UNET Froude Limit=0
UNET Froude Power=0
Write IC File=0
Echo Input=False
Echo Output=False
Write Detailed=0

--- NP13.f01 (steady flow) ---

Flow Title=NFF Regression Equation
Program Version=4.00
Number of Profiles= 1
Profile Names=P100yr
River Rch & RM=NP13,Main            ,2301.6
 622.933
River Rch & RM=NP13,Main            ,1902.8
682.6652
Boundary for River Rch & Prof#=NP13,Main            , 1
Up Type= 0
Dn Type= 3
Dn Slope=0.008031
DSS Import GetInterval= 0
DSS Import GetPeak= 0
DSS Import FillOption= 0

--- NP13.g01 (geometry) ---

Geom Title=USGS 3m DEM
Program Version=4.00

River Reach=NP13            ,Main
Reach XY= 30
      1736427.41      349605.378     1736421.981      349531.227
     1736396.589      349401.447     1736380.602      349352.545
     1736296.764       349202.04      1736248.98      349147.888
     1736197.218      349061.011     1736171.826      348969.789
     1736126.685      348717.754     1736102.448      348638.754
     1736056.153      348559.761     1736043.927      348495.812
     1736040.477      348395.259     1736024.843      348321.578
     1736019.226      348250.981     1735988.917      348203.082
     1735958.667      348161.653     1735913.535      348123.537
     1735871.101      348111.043     1735830.922      348076.117
     1735793.121      348021.875     1735754.274      347991.741
     1735707.253      347971.992     1735615.373      347914.328
     1735468.512      347912.501     1735453.407      347896.581
     1735411.137      347896.969     1735371.193      347887.689
     1735336.178      347868.776     1735297.225      347859.181

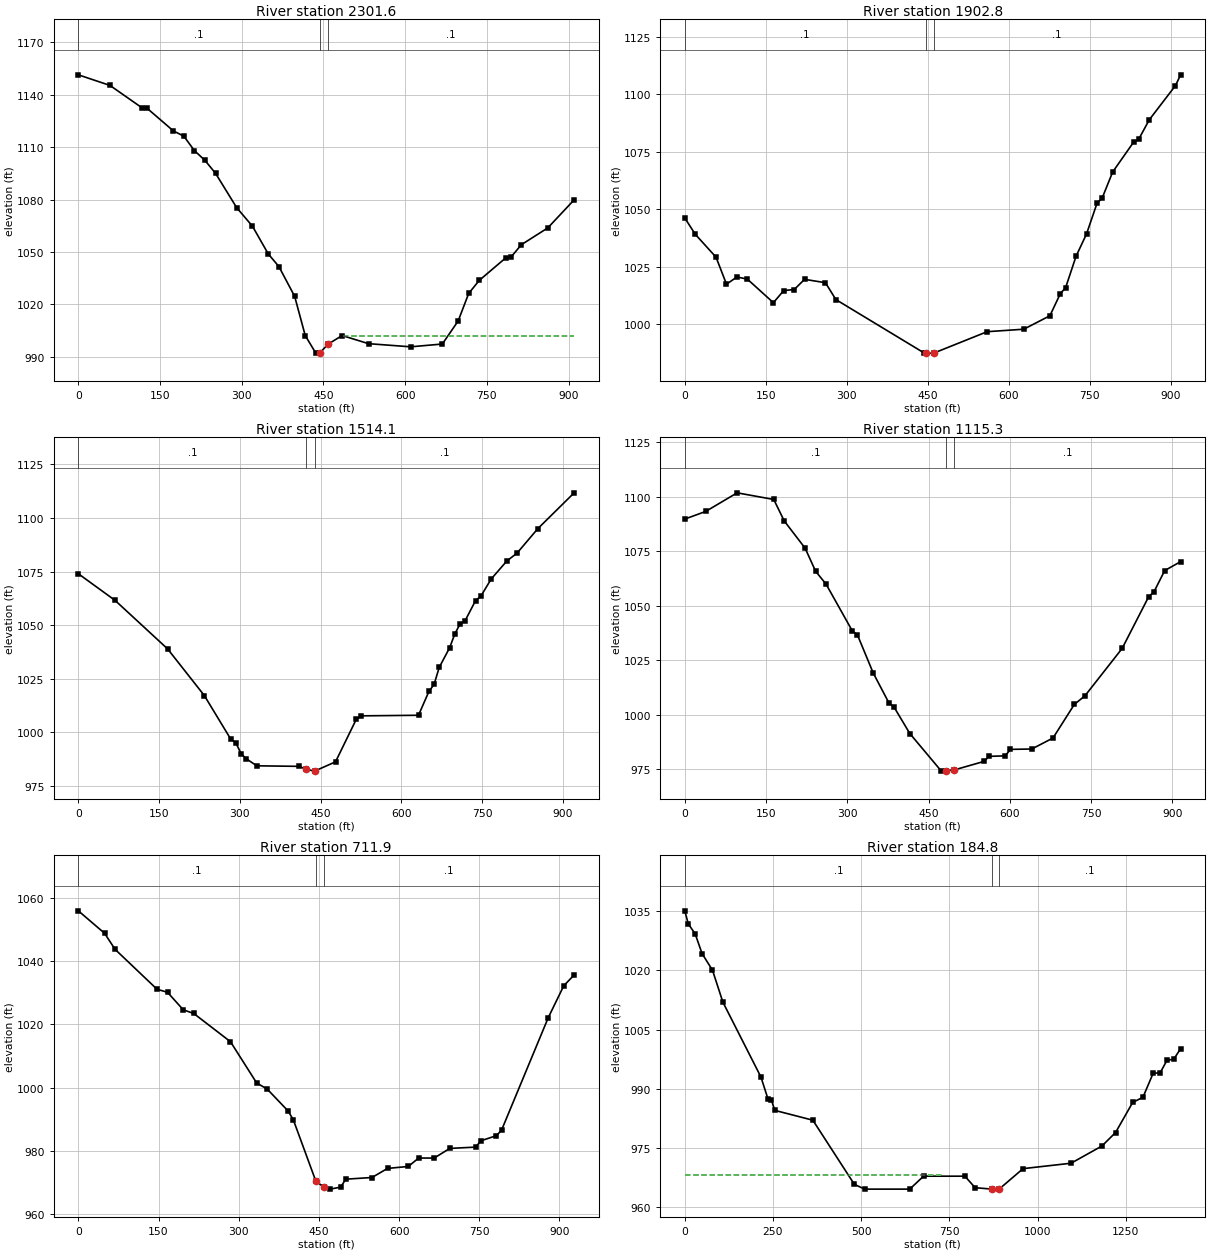
Type RM Length L Ch R = 1 ,2301.6  ,400.293,398.76,398.744
XS GIS Cut Line= 3
     1736835.385      349403.779     1736422.897      349596.454
     1736016.899      349801.753
#Sta/Elev= 30
       0 1151.35    58.1 1145.29   116.2 1132.63   125.9  1132.3   174.4 1119.29
   193.7 1116.25   213.1    1108   232.5 1102.38   251.9    1095   290.6  1075.4
   319.7 1064.73   348.7 1048.88   368.1 1041.71   397.1 1024.65   416.5 1002.24
   435.9  992.16   443.6  992.39   458.6  997.32   484.3 1002.23   532.7  997.57
   610.1  995.77   668.2  997.37   697.3 1010.58   716.6 1026.31     736 1033.77
   784.4 1046.59   794.1 1047.05   813.4  1054.2   861.8 1063.79   910.2 1079.86
#Mann= 3 , 0 , 0
       0      .1       0   443.6    .045       0   458.6      .1       0
#XS Ineff= 2 , 0
                          486.27         1002.16
Permanent Ineff=
       F       F
Bank Sta=443.6,458.6
XS Rating Curve= 0 ,0
Exp/Cntr=0.3,0.1

Type RM Length L Ch R = 1 ,1902.8  ,381.354,388.778,395.361
XS GIS Cut Line= 3
     1736700.626      348995.129     1736307.389      349220.573
     1735895.822      349436.482
#Sta/Elev= 30
       0 1046.24    19.3 1039.18    57.9 1029.18    77.2 1017.46    96.4  1020.6
   115.7  1019.7     164 1009.44   183.2 1014.71   202.5 1015.15   221.8 1019.58
   260.4 1018.12   279.7  1010.8   443.6  987.53   445.8  987.53   460.8  987.53
   559.8  996.84   627.6  997.92     676 1003.77   695.3 1013.39     705 1015.92
   724.4 1029.61   743.8 1039.31   763.1 1052.55   772.8 1054.92   792.2 1066.22
   830.9 1079.17   840.6 1080.53   859.9 1088.88   908.4 1103.73     918 1108.42
#Mann= 3 , 0 , 0
       0      .1       0   445.8    .045       0   460.8      .1       0
Bank Sta=445.8,460.8
XS Rating Curve= 0 ,0
Exp/Cntr=0.3,0.1

Type RM Length L Ch R = 1 ,1514.1  ,400.111,398.771,397.44
XS GIS Cut Line= 3
     1736576.355      348789.906     1736117.101      348879.193
     1735664.388       348883.34
#Sta/Elev= 30
       0 1073.99    68.2 1061.56   165.7 1038.94   233.9 1017.18   282.7  996.94
   292.4  995.09   302.2  990.08   311.9  987.65   331.4  984.38   409.4  984.13
   423.6  982.77   438.6   981.9   477.5  986.23     516 1006.05   525.6 1007.69
   631.6 1007.96   650.9 1019.07   660.5 1022.34   670.1 1030.32   689.4 1039.46
     699 1045.88   708.7 1050.58   718.3 1052.16   737.6 1061.49   747.2 1063.45
   766.5 1071.52   795.4 1079.89   814.6 1083.63   853.2 1095.04   920.6 1111.74
#Mann= 3 , 0 , 0
       0      .1       0   423.6    .045       0   438.6      .1       0
Bank Sta=423.6,438.6
XS Rating Curve= 0 ,0
Exp/Cntr=0.3,0.1

Type RM Length L Ch R = 1 ,1115.3  ,417.395,403.406,389.408
XS GIS Cut Line= 3
     1736496.195      348307.586     1736078.087      348484.263
     1735631.282      348598.625
#Sta/Elev= 30
       0 1089.79    38.6  1093.3    96.6 1101.84   164.2 1098.79   183.5 1088.94
   222.1 1076.42   241.4 1065.85   260.8  1059.9     309 1038.53   318.7 1036.59
   347.7 1019.17   376.6 1005.47   386.3 1003.44   415.3  991.36   473.5   974.1
   481.8  974.36   496.8  974.61     552  978.54   561.8  980.89   591.3  981.11
   601.1  984.09   640.4  984.25   679.6  989.31   718.9 1004.71   738.5 1008.66
   807.2 1030.43   856.2 1054.18     866 1056.44   885.7 1066.15   915.1 1070.26
#Mann= 3 , 0 , 0
       0      .1       0   481.8    .045       0   496.8      .1       0
Bank Sta=481.8,496.8
XS Rating Curve= 0 ,0
Exp/Cntr=0.3,0.1

Type RM Length L Ch R = 1 ,711.9   ,539.78,527.138,515.482
XS GIS Cut Line= 3
      1736212.27      347785.038     1735868.405      348188.189
     1735565.081      348445.311
#Sta/Elev= 30
       0 1055.96    49.1 1048.85    68.7 1043.77   147.2 1031.13   166.8 1030.17
   196.3 1024.62   215.9 1023.46   284.6 1014.52   333.6 1001.46   353.3  999.53
   392.5  992.57   402.3  989.73   443.9  970.55   458.9  968.43     471  967.85
   490.6  968.48   500.4     971   549.3  971.53   578.4  974.41   617.2  975.02
   636.6  977.69   665.7  977.69   694.8  980.74   743.2  981.15   752.9  983.15
     782  984.77   791.7  986.53     879 1022.12   908.1 1032.25   927.5 1035.65
#Mann= 3 , 0 , 0
       0      .1       0   443.9    .045       0   458.9      .1       0
Bank Sta=443.9,458.9
XS Rating Curve= 0 ,0
Exp/Cntr=0.3,0.1

Type RM Length L Ch R = 1 ,184.8   ,183.108,184.756,185.418
XS GIS Cut Line= 3
     1736211.649      347550.963     1735507.231      347726.324
     1735367.757      348391.424
#Sta/Elev= 30
       0 1035.07     9.8 1031.77    29.4 1029.23      49 1024.23    78.5 1020.03
   107.9 1011.95   215.8  992.97   235.4  987.52   245.2  987.22   255.1  984.52
     363  982.03   480.7  965.77   510.1  964.57   637.6  964.57   676.9  967.85
   793.9  967.85     823  964.93   871.5  964.57     891  964.57   958.9  969.76
  1094.8  971.13  1182.2  975.48    1221   978.9  1269.6  986.53  1298.7  987.84
  1327.8  993.96  1347.2  993.99  1366.7  997.19  1386.1   997.5  1405.5 1000.15
#Mann= 3 , 0 , 0
       0      .1       0   871.5    .045       0     891      .1       0
#XS Ineff= 2 , 0
          735.52  968.12
Permanent Ineff=
       F       F
Bank Sta=871.5,891
XS Rating Curve= 0 ,0
Exp/Cntr=0.3,0.1

Chan Stop Cuts=-1
Use User Specified Reach Order=0